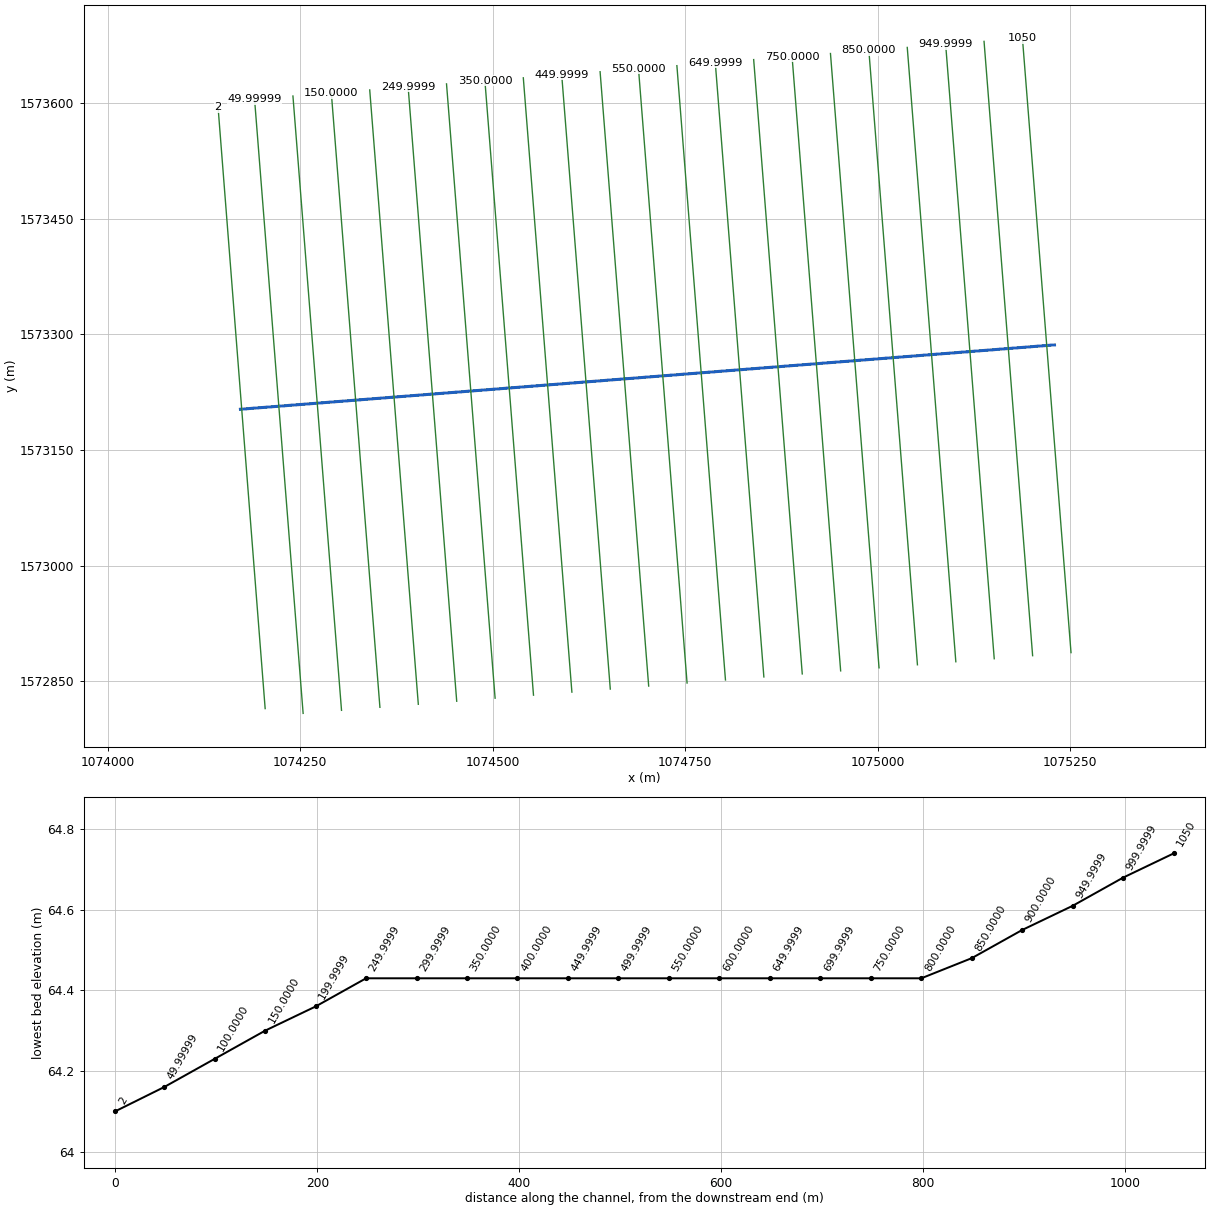
--- HECRAS_v0_Estructur.prj (project) ---

Proj Title=HECRAS_v0_EstructuraCanalPpalExpansion
Current Plan=p01
Default Exp/Contr=0.3,0.1
SI Units
Geom File=g01
Flow File=f01
Unsteady File=u01
Plan File=p01
Y Axis Title=Elevation
X Axis Title(PF)=Main Channel Distance
X Axis Title(XS)=Station
BEGIN DESCRIPTION:
END DESCRIPTION:
DSS File=dss
DSS Export Rating Curves= 0
DSS Export Rating Curve Sorted= 0
DSS Export Volume Flow Curves= 0
DXF OffsetX= 0
DXF OffsetY= 0
DXF ScaleX= 1
DXF ScaleY= 10

--- HECRAS_v0_Estructur.p01 (plan) ---

Plan Title=Steady
Program Version=6.70
Short Identifier=Steady2
Simulation Date=01SEP2008,00:15,02SEP2008,00:15
Geom File=g01
Flow File=u01
Subcritical Flow
K Sum by GR= 0
Std Step Tol= 0.01
Critical Tol= 0.01
Num of Std Step Trials= 20
Max Error Tol= 0.3
Flow Tol Ratio= 0.001
Split Flow NTrial= 30
Split Flow Tol= 0.02
Split Flow Ratio= 0.02
Log Output Level= 0
Friction Slope Method= 1
Unsteady Friction Slope Method= 2
Unsteady Bridges Friction Slope Method= 1
Parabolic Critical Depth
Global Vel Dist= 0 , 0 , 0
Global Log Level= 0
CheckData=True
Encroach Param=-1 ,0,0, 0
Flow Ratio Tolerance=0.1
Flow Ratio Min Ratio=0.5
Flow Ratio Max Ratio=4
Flow Ratio Max Iterations= 10
Computation Interval=1MIN
Output Interval=15MIN
Instantaneous Interval=15MIN
Mapping Interval=1HOUR
Computation Time Step Use Courant=        0
Computation Time Step Use Time Series=    0
Computation Time Step Count To Double=0
Computation Time Step Max Doubling=0
Computation Time Step Max Halving=0
Computation Time Step Residence Courant=0
Run HTab=-1
Run UNet=-1
Run Sediment= 0
Run PostProcess=-1
Run WQNet= 0
Run RASMapper= 0
UNET Theta= 1
UNET Theta Warmup= 1
UNET ZTol= 0.02
UNET ZSATol= 0.02
UNET MxIter= 20
UNET Max Iter WO Improvement= 0
UNET MaxInSteps= 0
UNET DtIC= 0
UNET DtMin= 0
UNET MaxCRTS= 20
UNET WFStab= 2
UNET SFStab= 1
UNET WFX= 1
UNET SFX= 1
UNET Gravity=32.17405
UNET 1D Methodology=Finite Difference
UNET DSS MLevel= 4
UNET Pardiso=0
UNET DZMax Abort= 100
UNET Use Existing IB Tables=-1
UNET Froude Reduction=False
UNET Froude Limit= 0.8
UNET Froude Power= 4
UNET D1 Cores= 0
UNET WindReference=Eulerian
UNET WindDragFormulation=Hsu (1988)
UNET D2 Coriolis=0
UNET D2 Cores= 0
UNET D2 Theta= 1
UNET D2 Theta Warmup= 1
UNET D2 Z Tol= 0.01
UNET D2 Volume Tol= 0.01
UNET D2 Max Iterations= 20
UNET D2 Advanced Convergence=0
UNET D2 WS Max Tol=0.15
UNET D2 WS RMS Tol=0.002
UNET D2 WS Stall Tol=1
UNET D2 Equation= 0
UNET D2 RampUpFraction=0.1
UNET D2 TimeSlices= 1
UNET D2 Turbulence Formulation=None
UNET D2 Eddy Viscosity=0.3
UNET D2 Transverse Eddy Viscosity=0.1
UNET D2 Smagorinsky Mixing=0.05
UNET D2 BCVolumeCheck=0
UNET D2 Cores=0
UNET D2 SolverType=PARDISO (Direct)
UNET D2 Minimum Iterations= 3
UNET D2 Maximum Iterations= 30
UNET D2 Restart Number= 10
UNET D2 Relaxation Coeff=1.3
UNET D2 SOR Precondition Iterations= 10
UNET D2 ILUT Maximum Fill= 8
UNET D2 ILUT Tolerance=1E-08
UNET D2 Convergence Tolerance=0.00001
Secondary Flow Approach=None
Spiral Intensity Factor=1
Spiral Intensity Adaptation Factor=1
Spiral Intensity Diffusion Factor=1
Momentum Dispersion Factor=1
Flow Smoothing Iterations=10
PS Theta= 1
PS WS Tol= 0.01
PS Volume Tol= 0.01
PS Max Iterations= 20
PS Equation= 0
PS Advance Time Step=-1
PS Target Courant=0.9
PS Time Slices= 1
PS Iterate With 2D=0
PS Project Initial WSE from DS=-1
PS Ramp Up Initial WSE from US=-1
PS Cores=0
UNET D1D2 MaxIter= 0
UNET D1D2 ZTol=0.01
UNET D1D2 QTol=0.1
UNET D1D2 MinQTol=1
DSS File=dss
Write IC File= 0
Write IC File at Fixed DateTime=0
Write IC File at Sim End=0
Echo Input=False
Echo Parameters=False
Echo Output=False
Write Detailed= 0
HDF Write Warmup=0
HDF Write Time Slices=0
HDF Flush=0
HDF Compression= 1
HDF Chunk Size= 1
HDF Spatial Parts= 1
HDF Use Max Rows=0
HDF Fixed Rows= 1
Calibration Method= 0
Calibration Iterations= 20
Calibration Max Change=0.05
Calibration Tolerance=0.2
Calibration Maximum=1.5
Calibration Minimum=0.5
Calibration Optimization Method= 1
WQ AD Non Conservative
WQ ULTIMATE=-1
WQ Max Comp Step=1HOUR
WQ Output Interval=15MIN
WQ Output Selected Increments= 0
WQ Create Restart=0
WQ Fixed Restart=0
WQ System Summary=0
WQ Write To DSS=0
Sorting and Armoring Iterations= 10
XS Update Threshold= 0.02
Bed Roughness Predictor= 0
Processes Affected by Predictor=Sediment Only
Hydraulics Update Threshold= 0.02
Energy Slope Method= 1
Volume Change Method= 1
Sediment Retention Method= 0
Sediment TS Multiplier= 1
Warm Up Method= 0
XS Weighting Method= 0
Number of US Weighted Cross Sections= 1
Number of DS Weighted Cross Sections= 1
Upstream XS Weight=0
Main XS Weight=1
Downstream XS Weight=0
Number of DS XS's Weighted with US Boundary= 1
Upstream Boundary Weight= 1
Weight of XSs Associated with US Boundary= 0
Number of US XS's Weighted with DS Boundary= 1
Downstream Boundary Weight= 0.5
Weight of XSs Associated with DS Boundary= 0.5
Percentile Method= 0
Sediment Output Level= 3
Mass or Volume Output= 0
Output Increment Type= 1
Profile and TS Output Increment= 1
Transport Output Increment 1
XS Output Flag= 0
XS Output Increment= 10
Read HDF5 Sediment Hotstart= 0
Sediment Hotstart Type= 0
Write Gradation File= 0
Read Gradation Hotstart= 0
Write HDF5 File= 1
Write Binary Output= 1
Write DSS Sediment File= 0
DSS Sediment Output Type= 1
SV Curve= 0
Specific Gage Flag= 0
Subcell Erosion Methods= 0
Subcell Deposition Methods= 0
Advection Scheme= 1
Matrix Solver= 0
Implicit Weighting Factor= 1
Maximum Outer Loop Convergence Iterations= 5
Convergence Maximum Absolute= 0.001
Convergence RMSE= 0.0001
Grain Fractions Max Abs Error= 0.001
Max Subgrid Regions= 1
Max Subgrid Length Scale= 3.402823E+38
Initial Layer Thickness= 3
Min Layer Thickness= 0.1
Max Layer Thickness= 6
Number of Layers= 5

--- HECRAS_v0_Estructur.f01 (steady flow) ---

Flow Title=Steady
Program Version=6.70
Number of Profiles= 7
Profile Names=Qtr2.33,Qtr5,Qtr10,Qtr25,Qtr50,Qtr100,Qm
River Rch & RM=Eje,Eje             ,1050
     130   205.9   275.3   369.9   445.1   522.1    1.92
Boundary for River Rch & Prof#=Eje,Eje             , 1
Up Type= 0
Dn Type= 3
Dn Slope=0.001322
Boundary for River Rch & Prof#=Eje,Eje             , 2
Up Type= 0
Dn Type= 3
Dn Slope=0.001322
Boundary for River Rch & Prof#=Eje,Eje             , 3
Up Type= 0
Dn Type= 3
Dn Slope=0.001322
Boundary for River Rch & Prof#=Eje,Eje             , 4
Up Type= 0
Dn Type= 3
Dn Slope=0.001322
Boundary for River Rch & Prof#=Eje,Eje             , 5
Up Type= 0
Dn Type= 3
Dn Slope=0.001322
Boundary for River Rch & Prof#=Eje,Eje             , 6
Up Type= 0
Dn Type= 3
Dn Slope=0.001322
Boundary for River Rch & Prof#=Eje,Eje             , 7
Up Type= 0
Dn Type= 3
Dn Slope=0.001322
DSS Import GetInterval= 0
DSS Import GetPeak= 0
DSS Import FillOption= 0

--- HECRAS_v0_Estructur.u01 (unsteady flow) ---

Flow Title=Unsteady
Program Version=6.70
Use Restart= 0
Initial Flow Loc=Eje             ,Eje             ,1050    ,0.0001
Boundary Location=Eje             ,Eje             ,1050    ,        ,                ,                ,                ,                                ,                                ,
Interval=1MIN
Flow Hydrograph= 4321
       0       0       0       0       0       0       0       0       0       0
       0       0       0       0       0       0       0       0       0       0
       0       0       0       0      .1      .1      .1      .1      .1      .1
      .1      .2      .2      .2      .3      .3      .3      .4      .4      .5
      .5      .6      .6      .7      .7      .8      .9       1     1.1     1.1
     1.2     1.3     1.4     1.5     1.7     1.8     1.9       2     2.2     2.3
     2.5     2.6     2.8     2.9     3.1     3.3     3.5     3.7     3.9     4.1
     4.3     4.5     4.7       5     5.2     5.4     5.7       6     6.2     6.5
     6.8     7.1     7.4     7.6       8     8.3     8.6     8.9     9.2     9.6
     9.9    10.3    10.6      11    11.3    11.7    12.1    12.5    12.9    13.3
    13.7    14.1    14.5    14.9    15.3    15.8    16.2    16.6    17.1    17.5
      18    18.5    18.9    19.4    19.9    20.4    20.8    21.3    21.8    22.3
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Stage Hydrograph TW Check=0
Use DSS=False
Use Fixed Start Time=False
Is Critical Boundary=False
Boundary Location=Eje             ,Eje             ,1       ,        ,                ,                ,                ,                                ,                                ,
Interval=1MIN
Flow Hydrograph= 4321
       0       0       0       0       0       0       0       0       0       0
       0       0       0       0       0       0       0       0       0       0
       0       0       0       0      .1      .1      .1      .1      .1      .1
      .1      .2      .2      .2      .3      .3      .3      .4      .4      .5
      .5      .6      .6      .7      .7      .8      .9       1     1.1     1.1
     1.2     1.3     1.4     1.5     1.7     1.8     1.9       2     2.2     2.3
     2.5     2.6     2.8     2.9     3.1     3.3     3.5     3.7     3.9     4.1
     4.3     4.5     4.7       5     5.2     5.4     5.7       6     6.2     6.5
     6.8     7.1     7.4     7.6       8     8.3     8.6     8.9     9.2     9.6
     9.9    10.3    10.6      11    11.3    11.7    12.1    12.5    12.9    13.3
    13.7    14.1    14.5    14.9    15.3    15.8    16.2    16.6    17.1    17.5
      18    18.5    18.9    19.4    19.9    20.4    20.8    21.3    21.8    22.3
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Stage Hydrograph TW Check=0
Use DSS=False
Use Fixed Start Time=False
Is Critical Boundary=False
Boundary Location=Eje             ,Eje             ,2       ,        ,                ,                ,                ,                                ,                                ,
Friction Slope=0.001322
Precipitation Mode=Disable
Wind Mode=No Wind Forces
Wave Mode=No Wave Forcing
Met BC=Precipitation|Expanded View=0
Met BC=Precipitation|Point Interpolation=Nearest
Met BC=Precipitation|Gridded Source=DSS
Met BC=Precipitation|Gridded Interpolation=
Met BC=Evapotranspiration|Expanded View=0
Met BC=Evapotranspiration|Point Interpolation=Nearest
Met BC=Evapotranspiration|Gridded Source=DSS
Met BC=Evapotranspiration|Gridded Interpolation=
Met BC=Wind Speed|Expanded View=0
Met BC=Wind Speed|Point Interpolation=Nearest
Met BC=Wind Speed|Gridded Source=DSS
Met BC=Wind Speed|Gridded Interpolation=
Met BC=Wind Direction|Expanded View=0
Met BC=Wind Direction|Point Interpolation=Nearest
Met BC=Wind Direction|Gridded Source=DSS
Met BC=Wind Direction|Gridded Interpolation=
Met BC=Wind Velocity X|Expanded View=0
Met BC=Wind Velocity X|Point Interpolation=Nearest
Met BC=Wind Velocity X|Gridded Source=DSS
Met BC=Wind Velocity X|Gridded Interpolation=
Met BC=Wind Velocity Y|Expanded View=0
Met BC=Wind Velocity Y|Point Interpolation=Nearest
Met BC=Wind Velocity Y|Gridded Source=DSS
Met BC=Wind Velocity Y|Gridded Interpolation=
Met BC=Wave Forcing X|Expanded View=0
Met BC=Wave Forcing X|Point Interpolation=Nearest
Met BC=Wave Forcing X|Gridded Source=DSS
Met BC=Wave Forcing X|Gridded Interpolation=
Met BC=Wave Forcing Y|Expanded View=0
Met BC=Wave Forcing Y|Point Interpolation=Nearest
Met BC=Wave Forcing Y|Gridded Source=DSS
Met BC=Wave Forcing Y|Gridded Interpolation=
Met BC=Air Density|Mode=Constant
Met BC=Air Density|Expanded View=0
Met BC=Air Density|Constant Value=1.225
Met BC=Air Density|Constant Units=kg/m3
Met BC=Air Density|Point Interpolation=Nearest
Met BC=Air Density|Gridded Source=DSS
Met BC=Air Density|Gridded Interpolation=
Met BC=Air Temperature|Expanded View=0
Met BC=Air Temperature|Point Interpolation=Nearest
Met BC=Air Temperature|Gridded Source=DSS
Met BC=Air Temperature|Gridded Interpolation=
Met BC=Humidity|Expanded View=0
Met BC=Humidity|Point Interpolation=Nearest
Met BC=Humidity|Gridded Source=DSS
Met BC=Humidity|Gridded Interpolation=
Met BC=Air Pressure|Mode=Constant
Met BC=Air Pressure|Expanded View=0
Met BC=Air Pressure|Constant Value=1013.2
Met BC=Air Pressure|Constant Units=mb
Met BC=Air Pressure|Point Interpolation=
Met BC=Air Pressure|Gridded Source=DSS
Met BC=Air Pressure|Gridded Interpolation=
Non-Newtonian Method= 0 ,
Non-Newtonian Constant Vol Conc=0
Non-Newtonian Yield Method= 0 ,
Non-Newtonian Yield Coef=0, 0
User Yeild=   0
Non-Newtonian Sed Visc= 0 ,
Non-Newtonian Obrian B=0
User Viscosity=0
User Viscosity Ratio=0
Herschel-Bulkley Coef=0, 0
Clastic Method= 0 ,
Coulomb Phi=0
Voellmy X=0
Non-Newtonian Hindered FV= 0
Non-Newtonian FV K=0
Non-Newtonian ds=0
Non-Newtonian Max Cv=0
Non-Newtonian Bulking Method= 0 ,
Non-Newtonian High C Transport= 0 ,
Lava Activation= 0
Temperature=1300,15,,15,14,980
Heat Ballance=1,1200,0.5,1,70,0.95
Viscosity=1000,,,
Profile Coefficient=4,1.3,
Lava Param=,2500,

--- HECRAS_v0_Estructur.g01 (geometry) ---

Geom Title=HECRAS_v0_EstructuraCanalPpalExpansion
Program Version=6.70

River Reach=Eje             ,Eje
Reach XY= 4
1075229.383063431573286.485036791074979.976866361573266.76186252
1074421.981627951573222.635354931074172.576016181573202.91227312

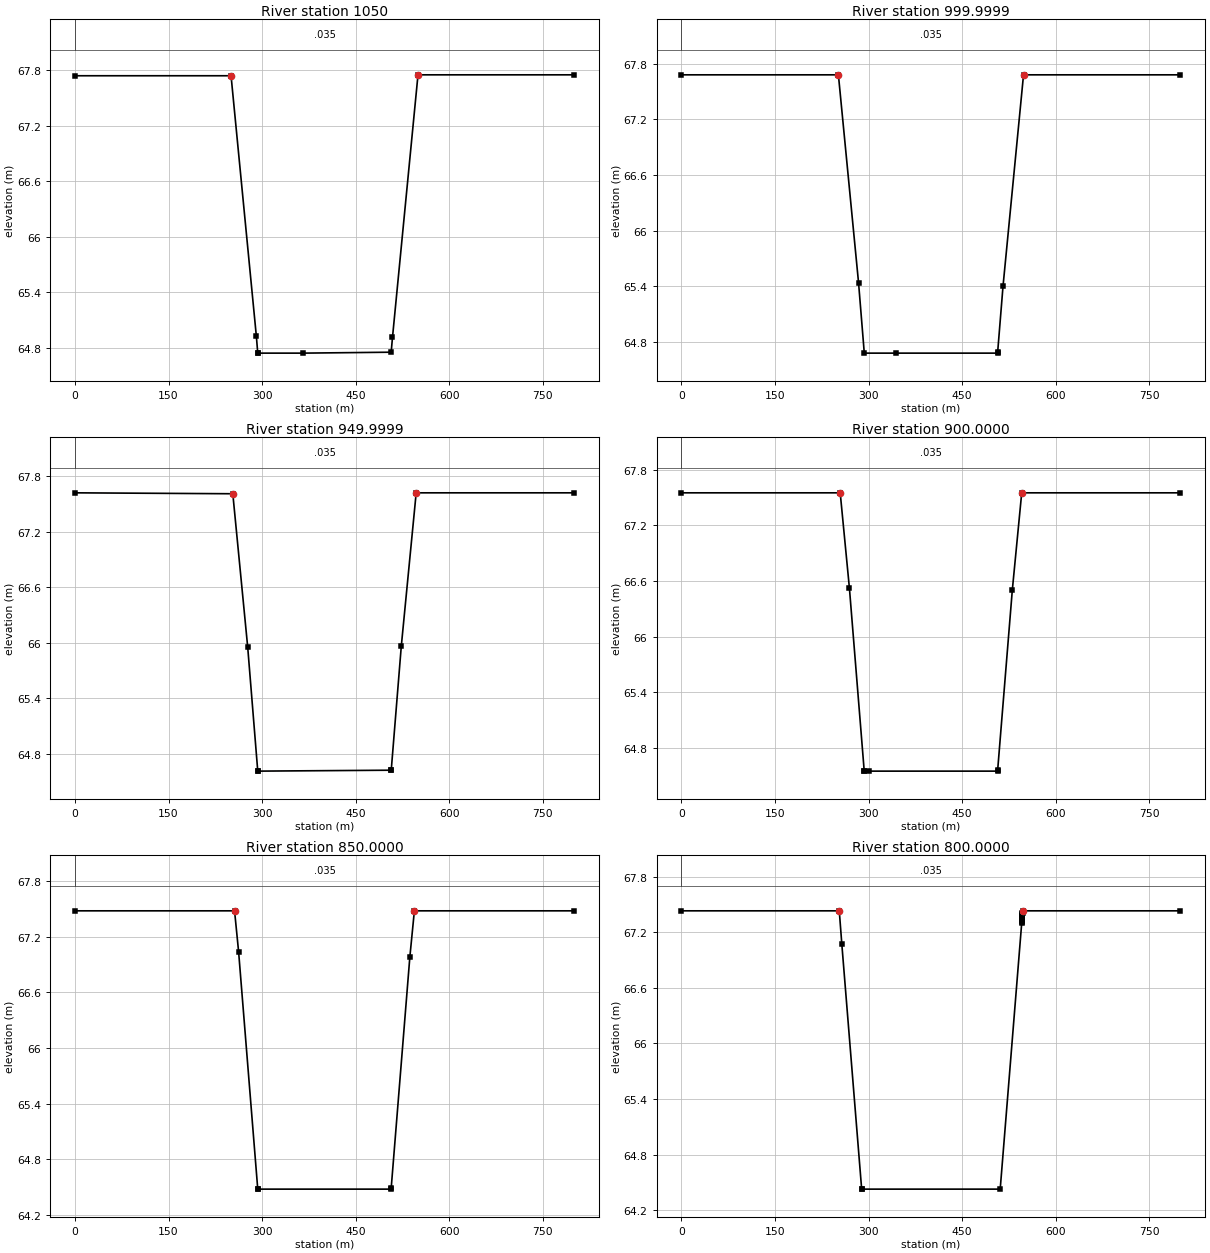
Type RM Length L Ch R = 1 ,1050    ,50,50,50
XS GIS Cut Line= 2
1075250.841873421572886.933214171075187.774396381573684.44339802
#Sta/Elev= 10
       0   67.74   250.2   67.74   290.8   64.92     293   64.74   293.1   64.74
   365.8   64.74   506.9   64.75     509   64.91   549.9   67.75     800   67.75
#Mann= 1 ,-1,0
       0    .035       0
Bank Sta=250.2,549.9
XS Rating Curve= 0 ,0
Exp/Cntr(USF)=0,0
Exp/Cntr=0.3,0.1

Type RM Length L Ch R = 1 ,999.9999,50,50,50
XS GIS Cut Line= 2
1075200.997484391572882.991493471075137.930012931573680.50167776
#Sta/Elev= 10
       0   67.68   251.6   67.68   283.9   65.44   293.1   64.68   344.1   64.68
   506.8   64.68   506.964.68828   515.5    65.4   548.4   67.68     800   67.68
#Mann= 1 ,-1,0
       0    .035       0
Bank Sta=251.6,548.4
XS Rating Curve= 0 ,0
Exp/Cntr(USF)=0,0
Exp/Cntr=0.3,0.1

Type RM Length L Ch R = 1 ,949.9999,50,50,50
XS GIS Cut Line= 2
1075151.153095671572879.049772791075088.085629171573676.55995747
#Sta/Elev= 10
       0   67.62     253   67.61   276.9   65.95     293   64.61   293.164.61001
   506.9   64.62     507   64.62   523.1   65.96     547   67.62     800   67.62
#Mann= 1 ,-1,0
       0    .035       0
Bank Sta=253,547
XS Rating Curve= 0 ,0
Exp/Cntr(USF)=0,0
Exp/Cntr=0.3,0.1

Type RM Length L Ch R = 1 ,900.0000,50,50,50
XS GIS Cut Line= 2
 1075101.30870721572875.108052121075038.241245161573672.61823716
#Sta/Elev= 11
       0   67.55   254.5   67.55   269.3   66.52     293   64.55   293.1   64.55
   300.6   64.55   506.8   64.55   506.964.55827   530.4    66.5   545.5   67.55
     800   67.55
#Mann= 1 ,-1,0
       0    .035       0
Bank Sta=254.5,545.5
XS Rating Curve= 0 ,0
Exp/Cntr(USF)=0,0
Exp/Cntr=0.3,0.1

Type RM Length L Ch R = 1 ,850.0000,50,50,50
XS GIS Cut Line= 2
1075051.464318961572871.166331481074988.396860921573668.67651683
#Sta/Elev= 10
       0   67.48   255.8   67.48   262.3   67.04     293   64.48   293.1   64.48
   506.8   64.48   506.964.48833   536.8   66.98   544.1   67.48     800   67.48
#Mann= 1 ,-1,0
       0    .035       0
Bank Sta=255.8,544.1
XS Rating Curve= 0 ,0
Exp/Cntr(USF)=0,0
Exp/Cntr=0.3,0.1

Type RM Length L Ch R = 1 ,800.0000,50,50,50
XS GIS Cut Line= 2
1075001.619930831572867.224611761074938.55247643 1573664.7347974
#Sta/Elev= 28
       0   67.43     253   67.43   257.1   67.07   288.9   64.43     289   64.43
     511   64.43   545.5    67.3   545.6   67.31   545.7   67.32   545.8   67.33
   545.9   67.34     546   67.34   546.1   67.35   546.2   67.35   546.2   67.36
   546.3   67.36   546.3   67.37   546.4   67.37   546.5   67.38   546.5   67.39
   546.6   67.39   546.6    67.4   546.7    67.4   546.7   67.41   546.8   67.41
   546.8   67.42   546.9   67.43     800   67.43
#Mann= 1 ,-1,0
       0    .035       0
Bank Sta=253,546.9
XS Rating Curve= 0 ,0
Exp/Cntr(USF)=0,0
Exp/Cntr=0.3,0.1

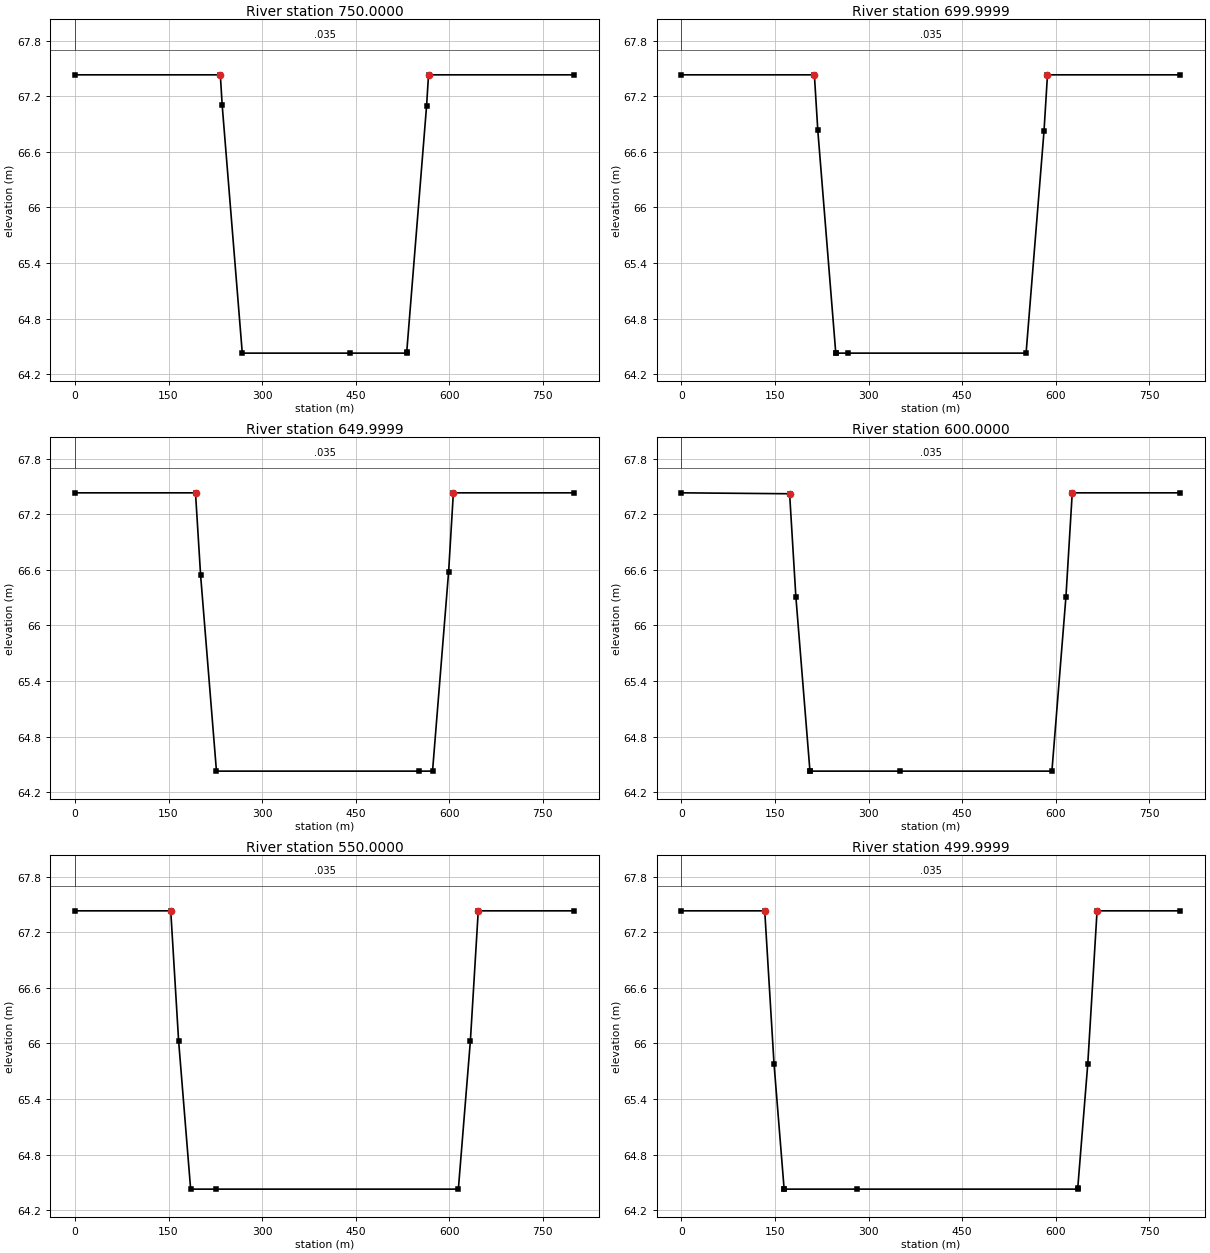
Type RM Length L Ch R = 1 ,750.0000,50,50,50
XS GIS Cut Line= 2
1074951.775544231572863.282895861074888.70808983 1573660.7930815
#Sta/Elev= 10
       0   67.43     233   67.43     236    67.1   268.2   64.43     441   64.43
   531.7   64.43   531.864.43834   563.6   67.09   566.8   67.43     800   67.43
#Mann= 1 ,-1,0
       0    .035       0
Bank Sta=233,566.8
XS Rating Curve= 0 ,0
Exp/Cntr(USF)=0,0
Exp/Cntr=0.3,0.1

Type RM Length L Ch R = 1 ,699.9999,50,50,50
XS GIS Cut Line= 2
1074901.931157631572859.341179961074838.86370322 1573656.8513656
#Sta/Elev= 10
       0   67.43   213.1   67.43   218.6   66.83   247.4   64.43   247.5   64.43
   267.7   64.43   552.5   64.43   581.2   66.82   586.8   67.43     800   67.43
#Mann= 1 ,-1,0
       0    .035       0
Bank Sta=213.1,586.8
XS Rating Curve= 0 ,0
Exp/Cntr(USF)=0,0
Exp/Cntr=0.3,0.1

Type RM Length L Ch R = 1 ,649.9999,50,50,50
XS GIS Cut Line= 2
1074852.086771031572855.399464061074789.01931662 1573652.9096497
#Sta/Elev= 9
       0   67.43   193.2   67.43   201.4   66.54   226.8   64.43   551.7   64.43
   573.2   64.43     599   66.58   606.6   67.43     800   67.43
#Mann= 1 ,-1,0
       0    .035       0
Bank Sta=193.2,606.6
XS Rating Curve= 0 ,0
Exp/Cntr(USF)=0,0
Exp/Cntr=0.3,0.1

Type RM Length L Ch R = 1 ,600.0000,50,50,50
XS GIS Cut Line= 2
1074802.242384421572851.457748161074739.17493002 1573648.9679338
#Sta/Elev= 10
       0   67.43   173.4   67.42   183.4   66.31     206   64.43   206.1   64.43
     350   64.43   593.9   64.43   616.4   66.31   626.5   67.43     800   67.43
#Mann= 1 ,-1,0
       0    .035       0
Bank Sta=173.4,626.5
XS Rating Curve= 0 ,0
Exp/Cntr(USF)=0,0
Exp/Cntr=0.3,0.1

Type RM Length L Ch R = 1 ,550.0000,50,50,50
XS GIS Cut Line= 2
1074752.397997821572847.516032261074689.33054342 1573645.0262179
#Sta/Elev= 9
       0   67.43   153.5   67.43   166.1   66.03   185.4   64.43   225.4   64.43
   614.6   64.43   633.9   66.03   646.5   67.43     800   67.43
#Mann= 1 ,-1,0
       0    .035       0
Bank Sta=153.5,646.5
XS Rating Curve= 0 ,0
Exp/Cntr(USF)=0,0
Exp/Cntr=0.3,0.1

Type RM Length L Ch R = 1 ,499.9999,50,50,50
XS GIS Cut Line= 2
1074702.553611221572843.574316361074639.48615681  1573641.084502
#Sta/Elev= 11
       0   67.43   133.5   67.43   148.4   65.78   164.6   64.43   164.7   64.43
   280.8   64.43   635.2   64.43   635.364.43833   651.4   65.78   666.3   67.43
     800   67.43
#Mann= 1 ,-1,0
       0    .035       0
Bank Sta=133.5,666.3
XS Rating Curve= 0 ,0
Exp/Cntr(USF)=0,0
Exp/Cntr=0.3,0.1

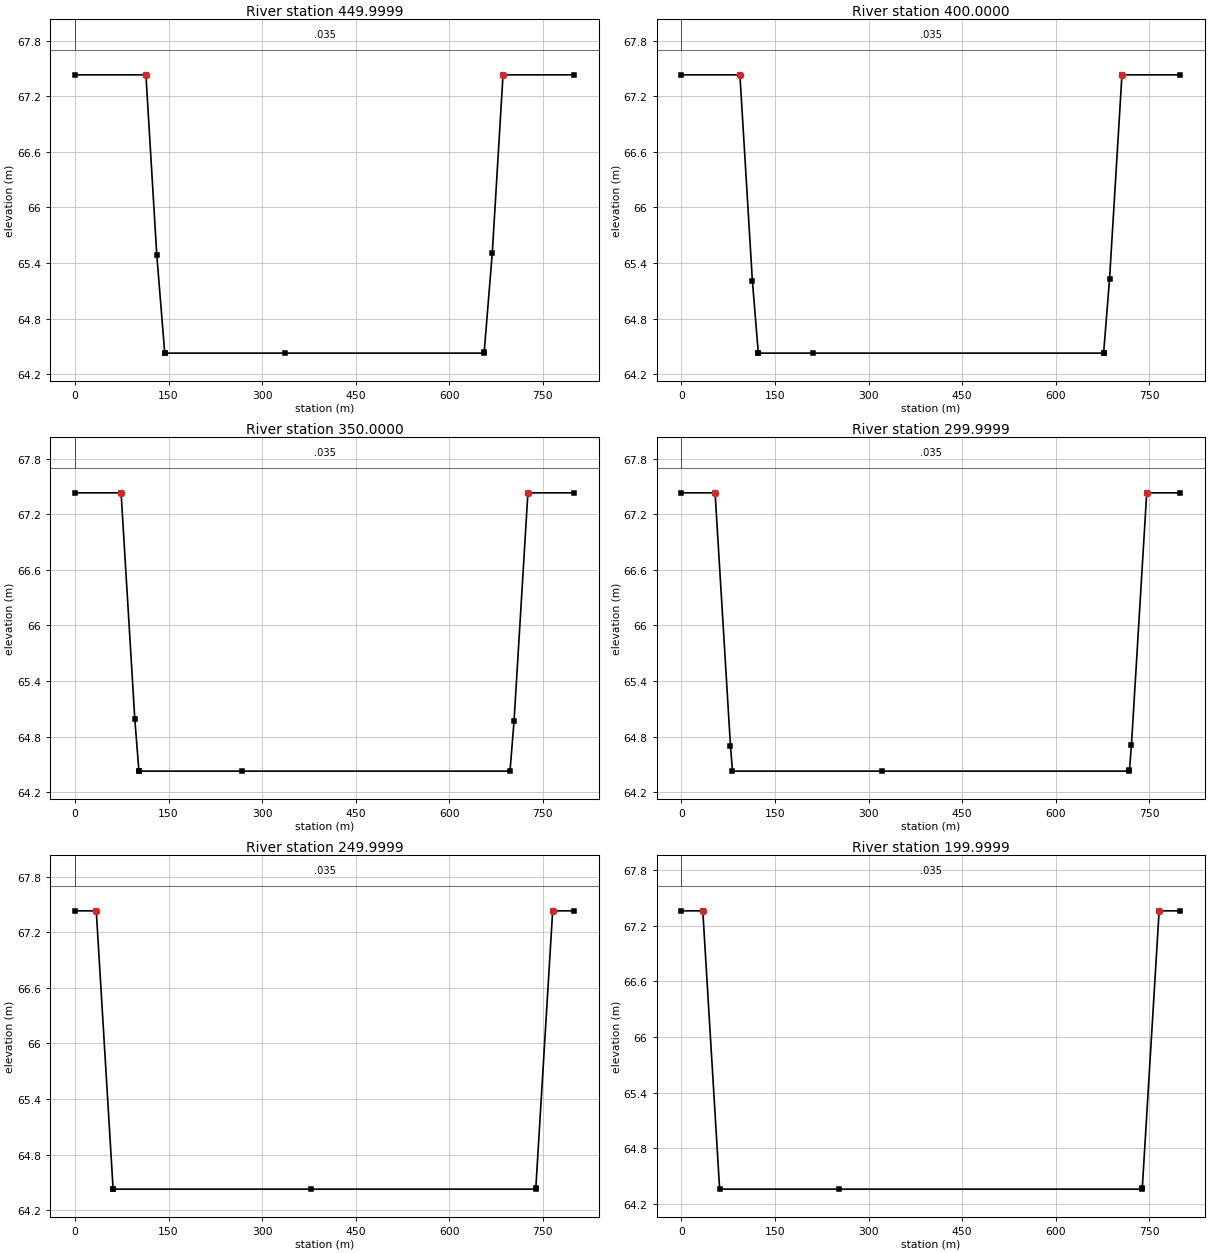
Type RM Length L Ch R = 1 ,449.9999,50,50,50
XS GIS Cut Line= 2
1074652.709224621572839.632600461074589.64177021 1573637.1427861
#Sta/Elev= 11
       0   67.43   113.7   67.43   131.1   65.49   143.9   64.43     144   64.43
   336.2   64.43   655.9   64.43     65664.43824     669   65.51   686.2   67.43
     800   67.43
#Mann= 1 ,-1,0
       0    .035       0
Bank Sta=113.7,686.2
XS Rating Curve= 0 ,0
Exp/Cntr(USF)=0,0
Exp/Cntr=0.3,0.1

Type RM Length L Ch R = 1 ,400.0000,50,50,50
XS GIS Cut Line= 2
1074602.864838011572835.690884561074539.79738361 1573633.2010702
#Sta/Elev= 11
       0   67.43    93.7   67.43   113.7   65.21   123.2   64.43   123.3   64.43
   211.6   64.43   676.7   64.43   676.8   64.43   686.3   65.23   706.2   67.43
     800   67.43
#Mann= 1 ,-1,0
       0    .035       0
Bank Sta=93.7,706.2
XS Rating Curve= 0 ,0
Exp/Cntr(USF)=0,0
Exp/Cntr=0.3,0.1

Type RM Length L Ch R = 1 ,350.0000,50,50,50
XS GIS Cut Line= 2
1074553.020451411572831.749168661074489.95299701 1573629.2593543
#Sta/Elev= 10
       0   67.43    73.9   67.43    95.9   64.99   102.5   64.43   102.6   64.43
     267   64.43   697.4   64.43   703.9   64.97   726.1   67.43     800   67.43
#Mann= 1 ,-1,0
       0    .035       0
Bank Sta=73.9,726.1
XS Rating Curve= 0 ,0
Exp/Cntr(USF)=0,0
Exp/Cntr=0.3,0.1

Type RM Length L Ch R = 1 ,299.9999,50,50,50
XS GIS Cut Line= 2
1074503.176064811572827.80745276 1074440.1086104 1573625.3176384
#Sta/Elev= 10
       0   67.43    53.9   67.43    78.6    64.7    81.8   64.43   322.3   64.43
   718.1   64.43   718.264.43849   721.4   64.71   745.9   67.43     800   67.43
#Mann= 1 ,-1,0
       0    .035       0
Bank Sta=53.9,745.9
XS Rating Curve= 0 ,0
Exp/Cntr(USF)=0,0
Exp/Cntr=0.3,0.1

Type RM Length L Ch R = 1 ,249.9999,50,50,50
XS GIS Cut Line= 2
1074453.331677851572823.865736851074390.264224151573621.37592254
#Sta/Elev= 9
       0   67.43    34.1   67.43    61.1   64.43    61.2   64.43   377.7   64.43
   738.7   64.43   738.864.44107   765.8   67.43     800   67.43
#Mann= 1 ,-1,0
       0    .035       0
Bank Sta=34.1,765.8
XS Rating Curve= 0 ,0
Exp/Cntr(USF)=0,0
Exp/Cntr=0.3,0.1

Type RM Length L Ch R = 1 ,199.9999,50,50,50
XS GIS Cut Line= 2
1074403.487289041572819.924025391074340.419839041573617.43421137
#Sta/Elev= 8
       0   67.36    34.2   67.36    61.2   64.36   253.1   64.36   738.7   64.36
   738.864.37107   765.8   67.36     800   67.36
#Mann= 1 ,-1,0
       0    .035       0
Bank Sta=34.2,765.8
XS Rating Curve= 0 ,0
Exp/Cntr(USF)=0,0
Exp/Cntr=0.3,0.1

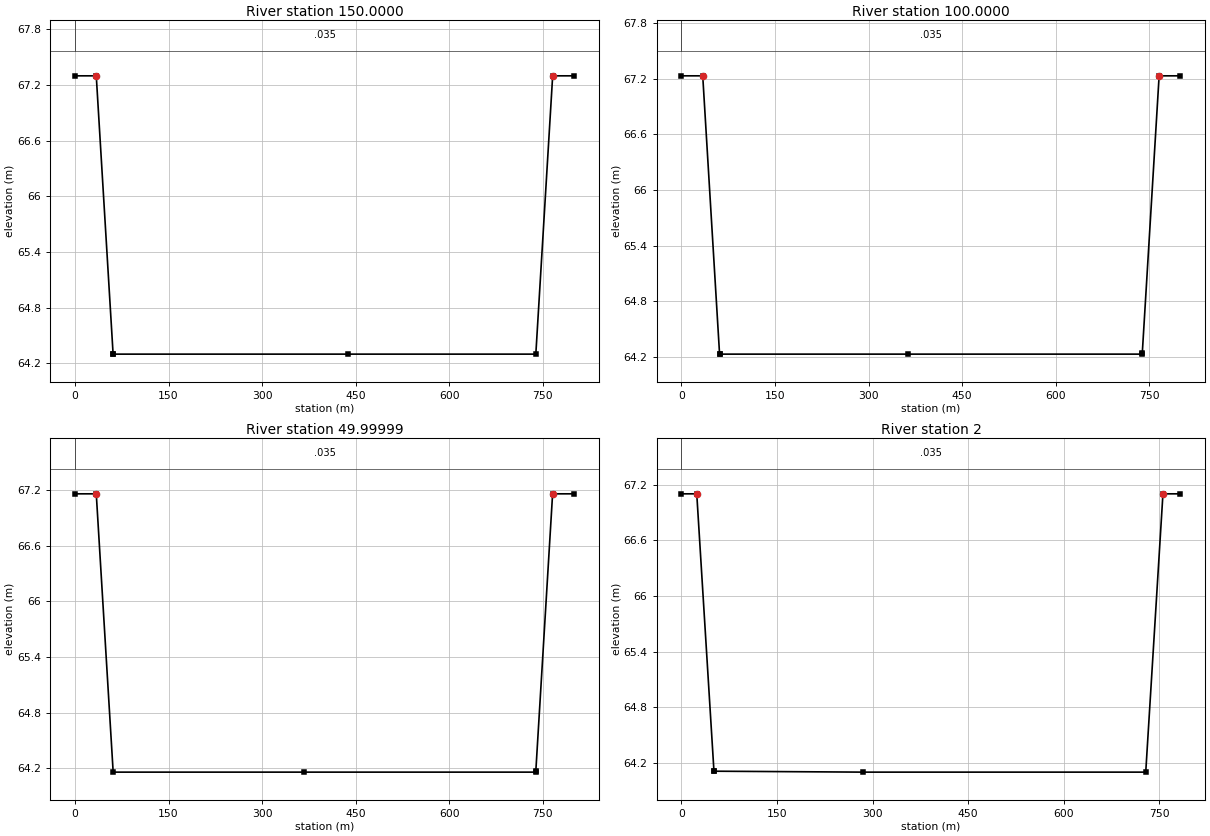
Type RM Length L Ch R = 1 ,150.0000,50,50,50
XS GIS Cut Line= 2
1074353.642900021572815.982313911074290.575454121573613.49250022
#Sta/Elev= 8
       0    67.3    34.1    67.3    61.1    64.3    61.2    64.3     437    64.3
   738.8    64.3   765.8    67.3     800    67.3
#Mann= 1 ,-1,0
       0    .035       0
Bank Sta=34.1,765.8
XS Rating Curve= 0 ,0
Exp/Cntr(USF)=0,0
Exp/Cntr=0.3,0.1

Type RM Length L Ch R = 1 ,100.0000,50,50,50
XS GIS Cut Line= 2
1074303.798510791572812.040602421074240.731069431573609.55078908
#Sta/Elev= 9
       0   67.23    34.1   67.23    61.1   64.23    61.2   64.23   363.8   64.23
   738.7   64.23   738.864.24107   765.8   67.23     800   67.23
#Mann= 1 ,-1,0
       0    .035       0
Bank Sta=34.1,765.8
XS Rating Curve= 0 ,0
Exp/Cntr(USF)=0,0
Exp/Cntr=0.3,0.1

Type RM Length L Ch R = 1 ,49.99999,48.3,48.3,48.3
XS GIS Cut Line= 2
1074253.95412128 1572808.09889091074190.886685011573605.60907797
#Sta/Elev= 8
       0   67.16    34.1   67.16    61.2   64.16   367.8   64.16   738.7   64.16
   738.864.17111   765.7   67.16     800   67.16
#Mann= 1 ,-1,0
       0    .035       0
Bank Sta=34.1,765.7
XS Rating Curve= 0 ,0
Exp/Cntr(USF)=0,0
Exp/Cntr=0.3,0.1

Type RM Length L Ch R = 1 ,2       ,,,
XS GIS Cut Line= 2
1074204.664783861572814.296584741074143.527069411573595.11253775
#Sta/Elev= 8
       0    67.1      24    67.1      51   64.11    51.164.10999   284.5    64.1
   728.7    64.1   755.7    67.1   783.2    67.1
#Mann= 1 ,-1,0
       0    .035       0
Bank Sta=24,755.7
XS Rating Curve= 0 ,0
Exp/Cntr(USF)=0,0
Exp/Cntr=0.3,0.1
LCMann Table=0

Chan Stop Cuts=-1
Use User Specified Reach Order=0
Composite Channel Slope=5